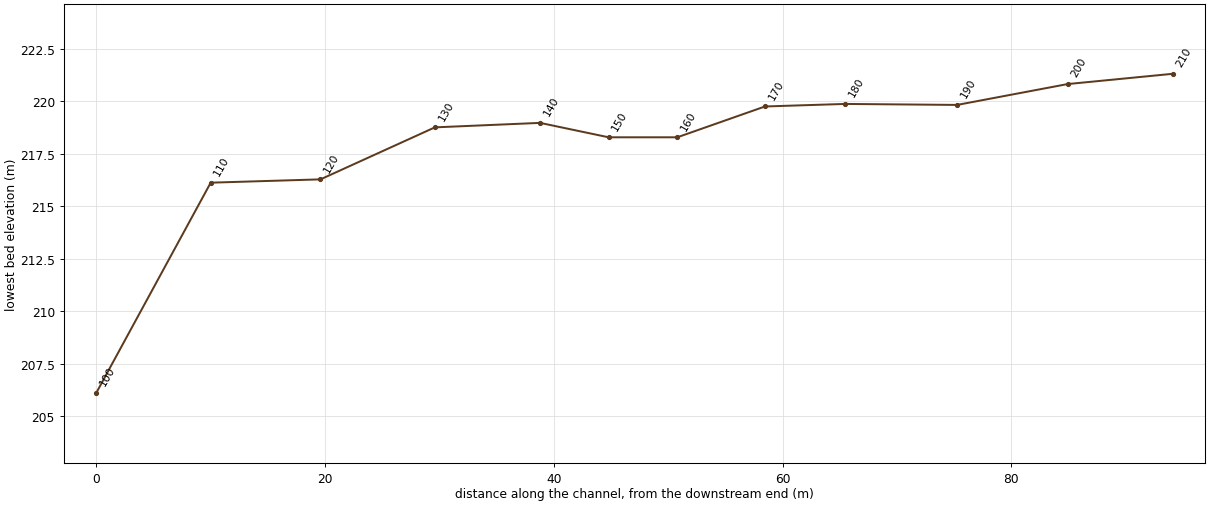
--- modele2.prj (project) ---

Proj Title=modele2
Current Plan=p01
Default Exp/Contr=0.3,0.1
SI Units
Geom File=g01
Flow File=f01
Plan File=p01
Y Axis Title=Elevation
X Axis Title(PF)=Main Channel Distance
X Axis Title(XS)=Station
BEGIN DESCRIPTION:
END DESCRIPTION:
DSS Export Rating Curves= 0
DSS Export Rating Curve Sorted= 0
DSS Export Volume Flow Curves= 0
DXF Filename=..\modele1.
DXF OffsetX= 0
DXF OffsetY= 0
DXF ScaleX= 1
DXF ScaleY= 10

--- modele2.p01 (plan) ---

Plan Title=Plan 01
Program Version=4.10
Short Identifier=Plan 01
Geom File=g01
Flow File=f01
Mixed Flow
K Sum by GR= 0
Std Step Tol= 0.003
Critical Tol= 0.003
Num of Std Step Trials= 40
Max Error Tol= 0.1
Flow Tol Ratio= 0.001
Split Flow NTrial= 60
Split Flow Tol= 0.006
Split Flow Ratio= 0.02
Log Output Level= 0
Friction Slope Method= 1
Unsteady Friction Slope Method= 2
Unsteady Bridges Friction Slope Method= 1
Parabolic Critical Depth
Global Vel Dist= 0 , 0 , 0
Global Log Level= 0
CheckData=Vrai
Encroach Param=-1 ,0,0, 0
Computation Interval=1HOUR
Output Interval=1HOUR
Run HTab= 0
Run UNet= 0
Run PostProcess= 0
Run WQNet= 0
UNET Theta= 1
UNET Theta Warmup= 1
UNET ZTol= 0.006
UNET ZSATol= 0.006
UNET MxIter= 20
UNET MaxInSteps= 0
UNET DtIC= 0
UNET DtMin= 0
UNET MaxCRTS= 20
UNET WFStab= 2
UNET SFStab= 1
UNET WFX= 1
UNET SFX= 1
UNET DSS MLevel= 4
UNET DZMax Abort= 30
UNET Convert EG Bridges= 0
UNET Use Existing IB Tables=-1
UNET Froude Reduction=Faux
UNET Froude Limit= 0.8
UNET Froude Power= 4
UNET Time Slicing=0,0, 5
UNET Junction Losses=0
Instantaneous Interval=1HOUR
Write IC File= 0
Write IC File at Sim End=0
Echo Input=Faux
Echo Parameters=Faux
Echo Output=Faux
Write Detailed= 0
WQ AD Non Conservative
WQ ULTIMATE=-1
WQ Max Comp Step=1HOUR
WQ Output Interval=15MIN
WQ Output Selected Increments= 0
WQ Output face flow=0
WQ Output face velocity=0
WQ Output face area=0
WQ Output face dispersion=0
WQ Output cell volume=0
WQ Output cell surface area=0
WQ Output cell continuity=0
WQ Output cumulative cell continuity=0
WQ Output face conc=0
WQ Output face dconc_dx=0
WQ Output face courant=0
WQ Output face peclet=0
WQ Output face adv mass=0
WQ Output face disp mass=0
WQ Output cell mass=0
WQ Output cell source sink temp=0
WQ Output cell source sink nsm=0
WQ Output MaxMinRange=-1
WQ Daily Max Min Mean=-1
WQ Daily Range=0
WQ Daily Time=0
WQ Create Restart=0
WQ Fixed Restart=0
WQ System Summary=0
WQ Use Fixed Temperature=0
Sorting and Armoring Iterations= 10
XS Update Threshold= 0.02
Hydraulics Update Threshold= 0.02
Energy Slope Method= 1
Volume Change Method= 1
XS Weighting Method= 0
Number of US Weighted Cross Sections= 1
Number of DS Weighted Cross Sections= 1
Upstream XS Weight=0
Main XS Weight=1
Downstream XS Weight=0
Number of DS XS's Weighted with US Boundary= 1
Upstream Boundary Weight= 1
Weight of XSs Associated with US Boundary= 0
Number of US XS's Weighted with DS Boundary= 1
Downstream Boundary Weight= 0.5
Weight of XSs Associated with DS Boundary= 0.5
Sediment Output Level= 4
Mass or Volume Output= 0
Output Increment Type= 1
Profile and TS Output Increment= 10
XS Output Flag= 0
XS Output Increment= 10
Disregard all LS=0
Disregard all Conn=0
Disregard all Breaches=0
Disregard all Pumps=0

--- modele2.f01 (steady flow) ---

Flow Title=modele1
Program Version=4.10
Number of Profiles= 14
Profile Names=PF 1,PF 2,PF 3,PF 4,PF 5,PF 6,PF 7,PF 8,PF 9,PF 10,PF 11,PF 12,PF 13,PF 14
River Rch & RM=Tinee,1               ,210
      10      20      30      50      70     100     200     300     400     500
     700     800     900    1000
Boundary for River Rch & Prof#=Tinee,1               , 1
Up Type= 3
Up Slope=0.01
Dn Type= 1
Dn Known WS=217
Boundary for River Rch & Prof#=Tinee,1               , 2
Up Type= 3
Up Slope=0.01
Dn Type= 1
Dn Known WS=217
Boundary for River Rch & Prof#=Tinee,1               , 3
Up Type= 3
Up Slope=0.01
Dn Type= 1
Dn Known WS=217
Boundary for River Rch & Prof#=Tinee,1               , 4
Up Type= 3
Up Slope=0.01
Dn Type= 1
Dn Known WS=217
Boundary for River Rch & Prof#=Tinee,1               , 5
Up Type= 3
Up Slope=0.01
Dn Type= 1
Dn Known WS=217
Boundary for River Rch & Prof#=Tinee,1               , 6
Up Type= 3
Up Slope=0.01
Dn Type= 1
Dn Known WS=217
Boundary for River Rch & Prof#=Tinee,1               , 7
Up Type= 3
Up Slope=0.01
Dn Type= 1
Dn Known WS=217
Boundary for River Rch & Prof#=Tinee,1               , 8
Up Type= 3
Up Slope=0.01
Dn Type= 1
Dn Known WS=217
Boundary for River Rch & Prof#=Tinee,1               , 9
Up Type= 3
Up Slope=0.01
Dn Type= 1
Dn Known WS=217
Boundary for River Rch & Prof#=Tinee,1               , 10
Up Type= 3
Up Slope=0.01
Dn Type= 1
Dn Known WS=217
Boundary for River Rch & Prof#=Tinee,1               , 11
Up Type= 3
Up Slope=0.01
Dn Type= 1
Dn Known WS=217
Boundary for River Rch & Prof#=Tinee,1               , 12
Up Type= 3
Up Slope=0.01
Dn Type= 1
Dn Known WS=217
Boundary for River Rch & Prof#=Tinee,1               , 13
Up Type= 3
Up Slope=0.01
Dn Type= 1
Dn Known WS=217
Boundary for River Rch & Prof#=Tinee,1               , 14
Up Type= 3
Up Slope=0.01
Dn Type= 1
Dn Known WS=217
DSS Import GetInterval= 0
DSS Import GetPeak= 0
DSS Import FillOption= 0

--- modele2.g01 (geometry) ---

Geom Title=modele1
Program Version=4.10

River Reach=Tinee           ,1
Reach XY= 3
0.013986013986010.727272727272730.286713286713290.21445221445221
0.310023310023310.17482517482518

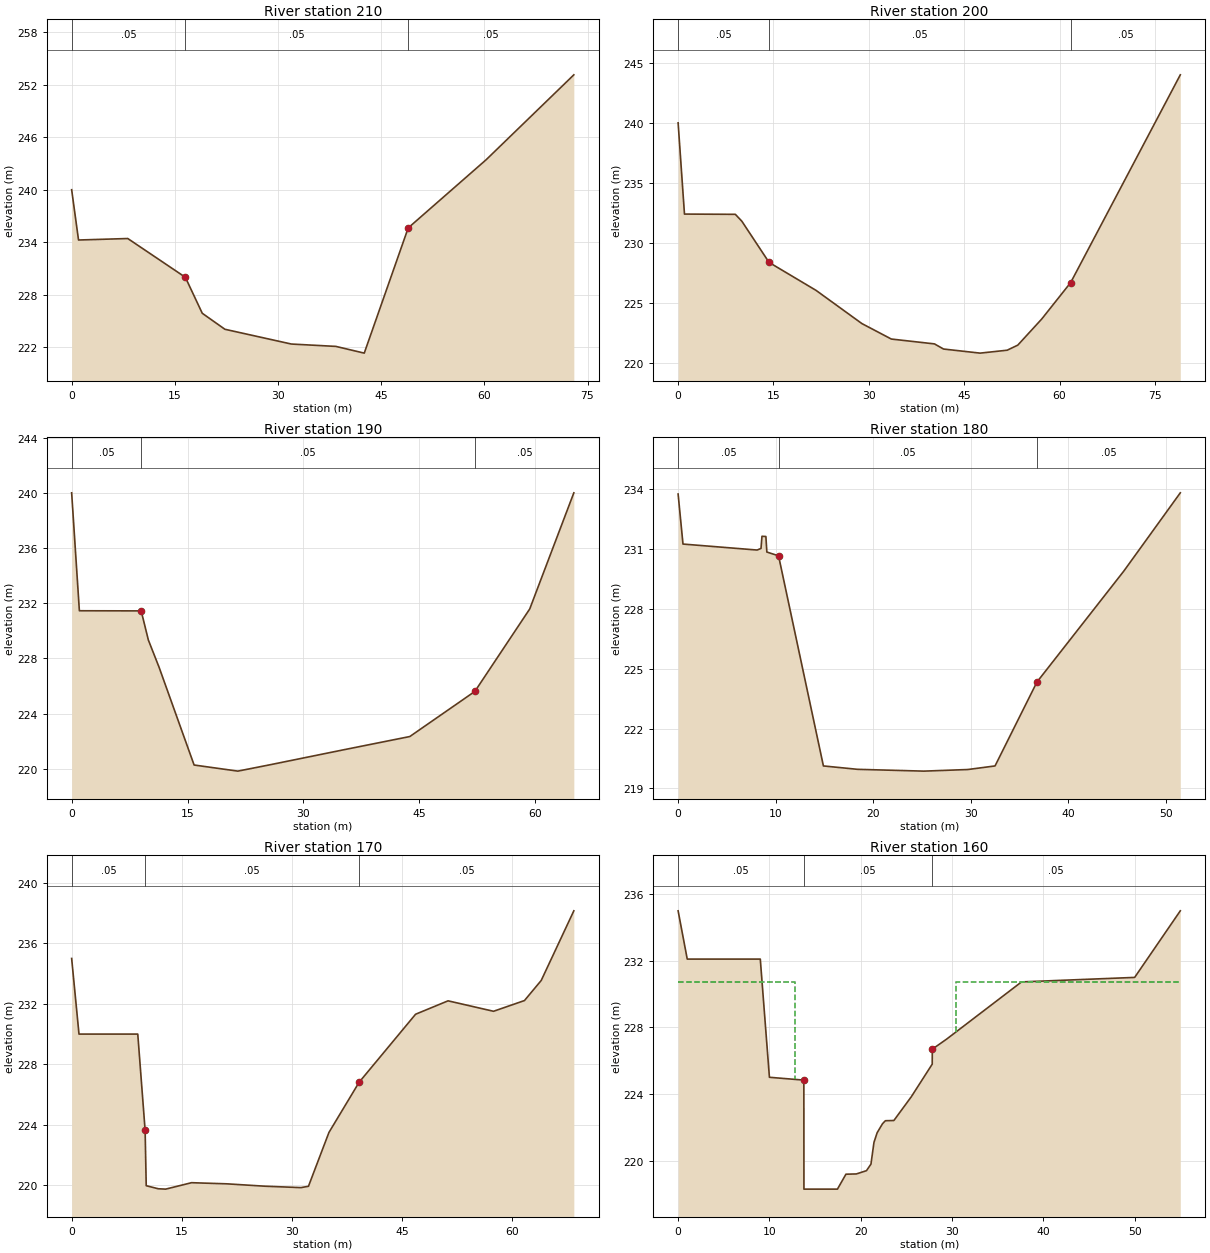
Type RM Length L Ch R = 1 ,210     ,9.222,9.222,9.222
#Sta/Elev= 12
       0     240       1 234.247    8.16 234.417   16.53 229.984   18.99 225.865
   22.28 224.035   31.94 222.346   38.41 222.075   42.54 221.306   48.93 235.631
   60.27 243.437   73.01 253.145
#Mann= 3 , 0 , 0
       0     .05       0   16.53     .05       0   48.93     .05       0
Bank Sta=16.53,48.93
XS Rating Curve= 0 ,0
Exp/Cntr=0.3,0.1

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
Type RM Length L Ch R = 1 ,200     ,9.667,9.667,9.667
#Sta/Elev= 16
       0     240       1   232.4       9 232.379   10.02 231.809   14.31 228.372
   21.69 226.046   28.91 223.277   33.54 221.989   40.32 221.585   41.75 221.157
    47.5 220.816   51.76 221.059   53.43 221.483   57.18 223.649   61.75 226.697
   78.99 244.001
#Mann= 3 , 0 , 0
       0     .05       0   14.31     .05       0   61.75     .05       0
Bank Sta=14.31,61.75
XS Rating Curve= 0 ,0
Exp/Cntr=0.3,0.1

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
Type RM Length L Ch R = 1 ,190     ,9.8,9.8,9.8
#Sta/Elev= 13
       0     240       1  231.45       9  231.44    9.93 229.327   11.31 227.363
   15.85 220.266   21.51 219.823   25.74 220.291   34.73 221.316   43.77 222.331
   52.19 225.602   59.29 231.579      65     240
#Mann= 3 , 0 , 0
       0     .05       0       9     .05       0   52.19     .05       0
Bank Sta=9,52.19
XS Rating Curve= 0 ,0
Exp/Cntr=0.3,0.1

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
Type RM Length L Ch R = 1 ,180     ,7,7,7
#Sta/Elev= 16
       0  233.77      .5  231.26     8.1  230.96     8.5  231.04     8.6  231.65
       9  231.64     9.1  230.86    10.3  230.67    14.9  220.13    18.4  219.96
    25.2  219.87    29.7  219.95    32.5  220.13    36.8  224.34    45.7   229.9
    51.5  233.83
#Mann= 3 , 0 , 0
       0     .05       0    10.3     .05       0    36.8     .05       0
Bank Sta=10.3,36.8
XS Rating Curve= 0 ,0
Exp/Cntr=0.3,0.1

Type RM Length L Ch R = 1 ,170     ,7.667,7.667,7.667
#Sta/Elev= 20
       0     235       1     230       9     230      10 223.627   10.15 219.975
   11.79 219.773    12.8 219.749   16.32 220.174   21.13 220.099    26.3 219.942
    31.2 219.849   32.23 219.936   35.02 223.497   39.13 226.818   46.81 231.312
   51.23 232.199   57.42 231.508   61.63 232.217   63.91 233.545   68.35  238.15
#Mann= 3 , 0 , 0
       0     .05       0      10     .05       0   39.13     .05       0
Bank Sta=10,39.13
XS Rating Curve= 0 ,0
Exp/Cntr=0.3,0.1

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
Type RM Length L Ch R = 1 ,160     ,6,6,6
#Sta/Elev= 23
       0     235       1   232.1       9   232.1      10     225   13.77  224.83
   13.78 218.282   17.45 218.282   18.38 219.179   19.52 219.194   20.63 219.391
   21.12 219.782   21.45  221.09    21.8 221.672   22.39 222.213    22.7 222.391
   23.63 222.404   25.54 223.832   27.83  225.79   27.84  226.69    29.4  227.29
  37.612  230.73      50     231      55     235
#Mann= 3 , 0 , 0
       0     .05       0   13.77     .05       0   27.84     .05       0
#XS Ineff= 2 , 0
       0   12.78  230.73    30.4       0  230.73
Permanent Ineff=
       F       F
Bank Sta=13.77,27.84
XS Rating Curve= 0 ,0
Exp/Cntr=0.5,0.3

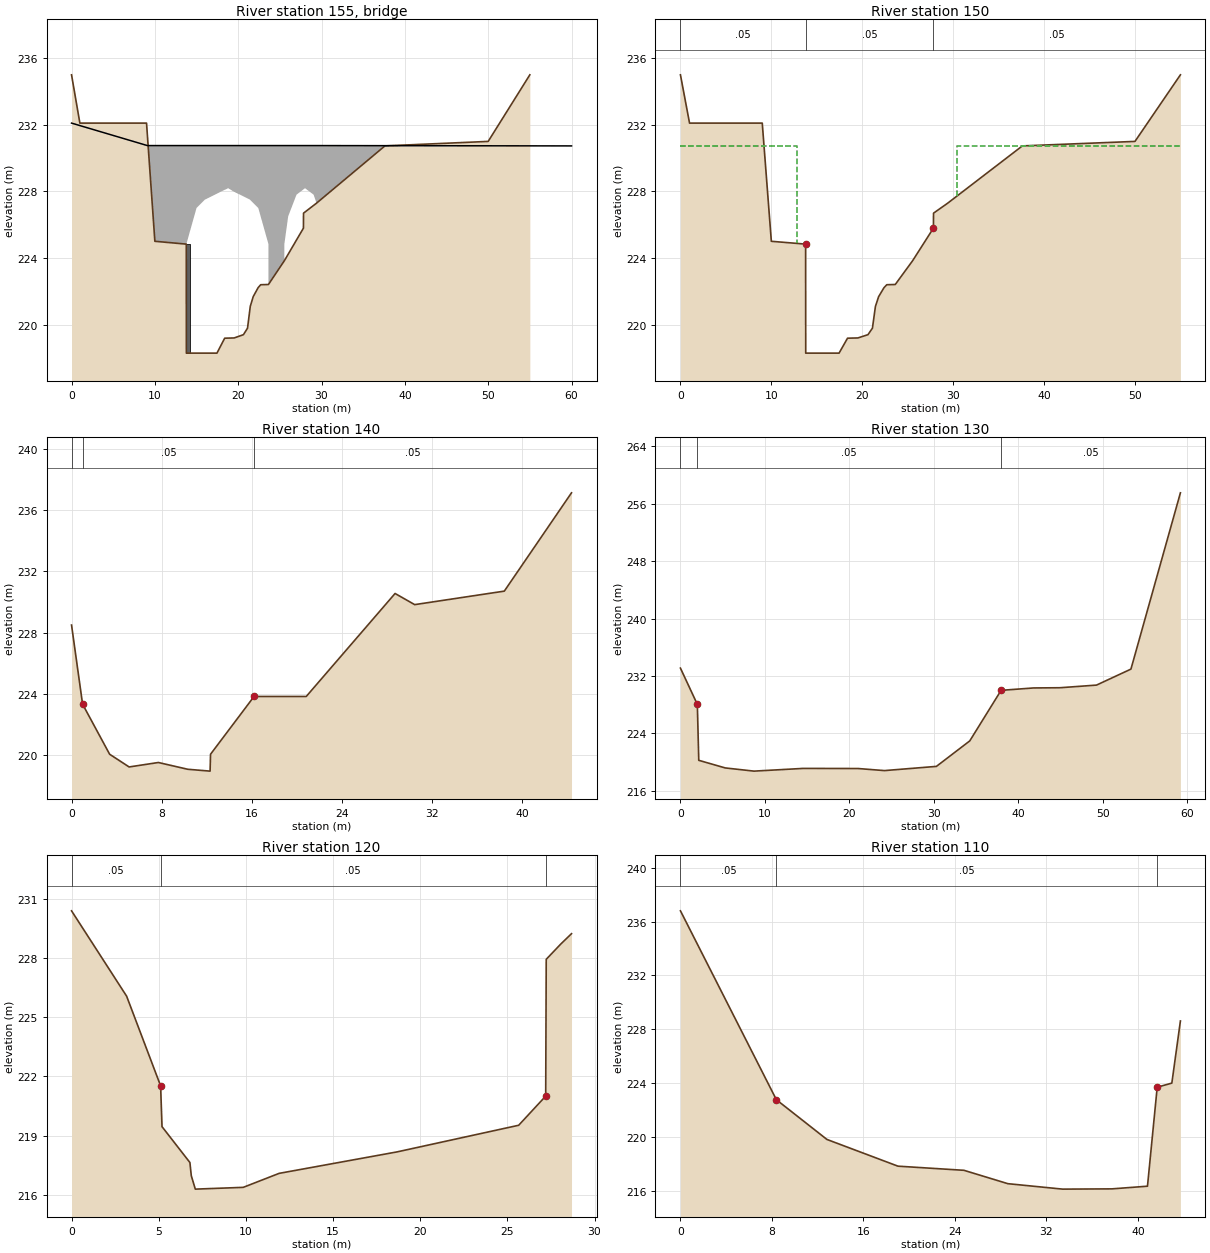
Type RM Length L Ch R = 3 ,155     ,,,
Bridge Culvert--1,0,-1,-1, 0
Deck Dist Width WeirC Skew NumUp NumDn MinLoCord MaxHiCord MaxSubmerge Is_Ogee
1,4,1.71,0, 21, 21, 230.73, , 0.98, 0, 0,0,,
       0     9.1      10   13.78      15      16      18    18.8   19.41   21.41
   22.41   23.63   23.63   25.54   25.54      26      27   28.02   29.05    29.4
      60
   232.1  230.75  230.75  230.75  230.75  230.75  230.75  230.75  230.75  230.75
  230.75  230.75  230.75  230.75  230.75  230.75  230.75  230.75  230.75  230.75
  230.73
     218  230.75     225  224.83     227   227.5     228  228.19     228   227.5
     227  224.83   222.4  223.83  224.83   226.5   227.8  228.19   227.8  227.29
  230.73
       0     9.1      10   13.78      15      16      18    18.8   19.41   21.41
   22.41   23.63   23.63   25.54   25.54      26      27   28.02   29.05    29.4
      60
   232.1  230.75  230.75  230.75  230.75  230.75  230.75  230.75  230.75  230.75
  230.75  230.75  230.75  230.75  230.75  230.75  230.75  230.75  230.75  230.75
  230.73
     218  230.75     225  224.83     227   227.5     228  228.19     228   227.5
     227  224.83   222.4  223.83  224.83   226.5   227.8  228.19   227.8  227.29
  230.73
Pier Skew, UpSta & Num, DnSta & Num=  ,14, 2 ,14, 2 , 0 , 0 , 0 ,,
     .44     .44
  218.28  224.83
     .44     .44
  218.28  224.83
BR Coef=-1 , 0 , 0 ,, 0 ,,,0.8,0,,0,
WSPro=,,,, 1 ,,,, 0 ,,,, 0 ,,,,-1 ,-1 ,-1 , 0 , 0 , 0 , 0 , 0
BC Design=,, 0 ,, 0 ,,,,,,
BC Use User HTab Curves=0
BC User HTab FreeFlow(D)= 0

Type RM Length L Ch R = 1 ,150     ,6,6,6
#Sta/Elev= 23
       0     235       1   232.1       9   232.1      10     225   13.77  224.83
   13.78 218.282   17.45 218.282   18.38 219.179   19.52 219.194   20.63 219.391
   21.12 219.782   21.45  221.09    21.8 221.672   22.39 222.213    22.7 222.391
   23.63 222.404   25.54 223.832   27.83  225.79   27.84  226.69    29.4  227.29
  37.612  230.73      50     231      55     235
#Mann= 3 , 0 , 0
       0     .05       0   13.77     .05       0   27.83     .05       0
#XS Ineff= 2 , 0
       0   12.78  230.73    30.4       0  230.73
Permanent Ineff=
       F       F
Bank Sta=13.77,27.83
XS Rating Curve= 0 ,0
Exp/Cntr=0.5,0.3

Type RM Length L Ch R = 1 ,140     ,9.2,9.2,9.2
#Sta/Elev= 14
       0 228.503     .98 223.338    3.38  220.07    5.11  219.24     7.7 219.531
   10.31 219.089   12.29 218.968   12.33  220.07   16.19  223.84   20.82 223.841
    28.7 230.563   30.44 229.835   38.39 230.717   44.35 237.133
#Mann= 3 , 0 , 0
       0     .05       0     .98     .05       0   16.19     .05       0
Bank Sta=0.98,16.19
XS Rating Curve= 0 ,0
Exp/Cntr=0.3,0.1

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
Type RM Length L Ch R = 1 ,130     ,10,10,10
#Sta/Elev= 16
       0 233.096       2 228.049    2.17  220.26    5.31 219.199    8.71 218.755
   14.55 219.134   21.04 219.117   24.16 218.828   30.32 219.415   34.27 222.965
   37.98 230.003   41.83 230.337   44.94 230.366   49.28 230.734   53.36 232.961
   59.22 257.507
#Mann= 3 , 0 , 0
       0     .05       0       2     .05       0   37.98     .05       0
Bank Sta=2,37.98
XS Rating Curve= 0 ,0
Exp/Cntr=0.3,0.1

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
Type RM Length L Ch R = 1 ,120     ,9.6,9.6,9.6
#Sta/Elev= 15
       0   230.4    3.16  226.07    5.11  221.52    5.19  219.45    6.79  217.63
    6.87  216.96     7.1  216.28    9.85  216.37   11.91  217.08   18.68  218.17
   25.65  219.52    27.2     221   27.23  227.94   28.06  228.71   28.68  229.24
#Mann= 3 , 0 , 0
       0     .05       0    5.11     .05       0    27.2     .05       0
Bank Sta=5.11,27.2
XS Rating Curve= 0 ,0
Exp/Cntr=0.3,0.1

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
Type RM Length L Ch R = 1 ,110     ,10,10,10
#Sta/Elev= 12
       0 236.799    8.39 222.764   12.81 219.813   19.02 217.828   24.79  217.52
   28.63 216.527   33.42 216.122   37.73 216.141   40.84  216.34   41.69 223.694
   42.97 223.999   43.72 228.615
#Mann= 3 , 0 , 0
       0     .05       0    8.39     .05       0   41.69     .05       0
Bank Sta=8.39,41.69
XS Rating Curve= 0 ,0
Exp/Cntr=0.3,0.1

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
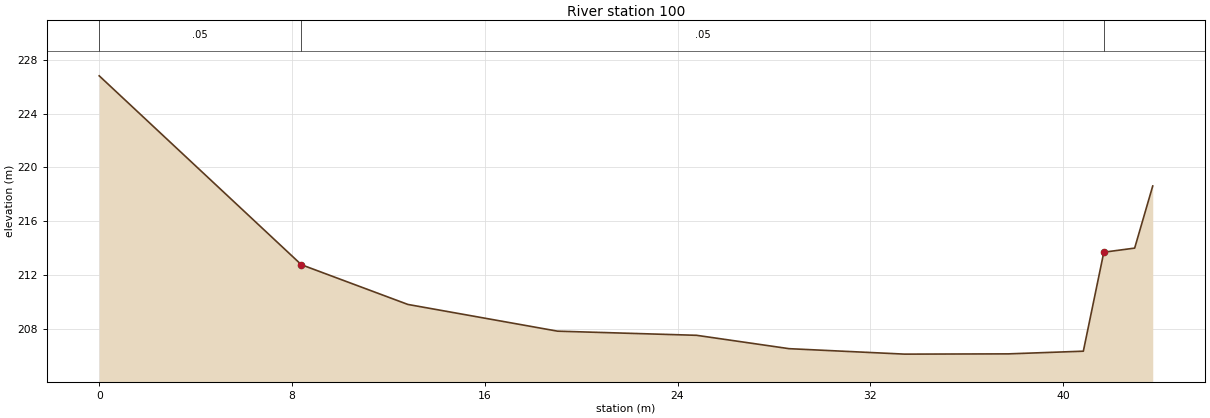
Type RM Length L Ch R = 1 ,100     ,0,0,0
#Sta/Elev= 12
       0 226.799    8.39 212.764   12.81 209.813   19.02 207.828   24.79  207.52
   28.63 206.527   33.42 206.122   37.73 206.141   40.84  206.34   41.69 213.694
   42.97 213.999   43.72 218.615
#Mann= 3 , 0 , 0
       0     .05       0    8.39     .05       0   41.69     .05       0
Bank Sta=8.39,41.69
XS Rating Curve= 0 ,0
Exp/Cntr=0.3,0.1

Chan Stop Cuts=-1
Use User Specified Reach Order=0
Composite Channel Slope=5